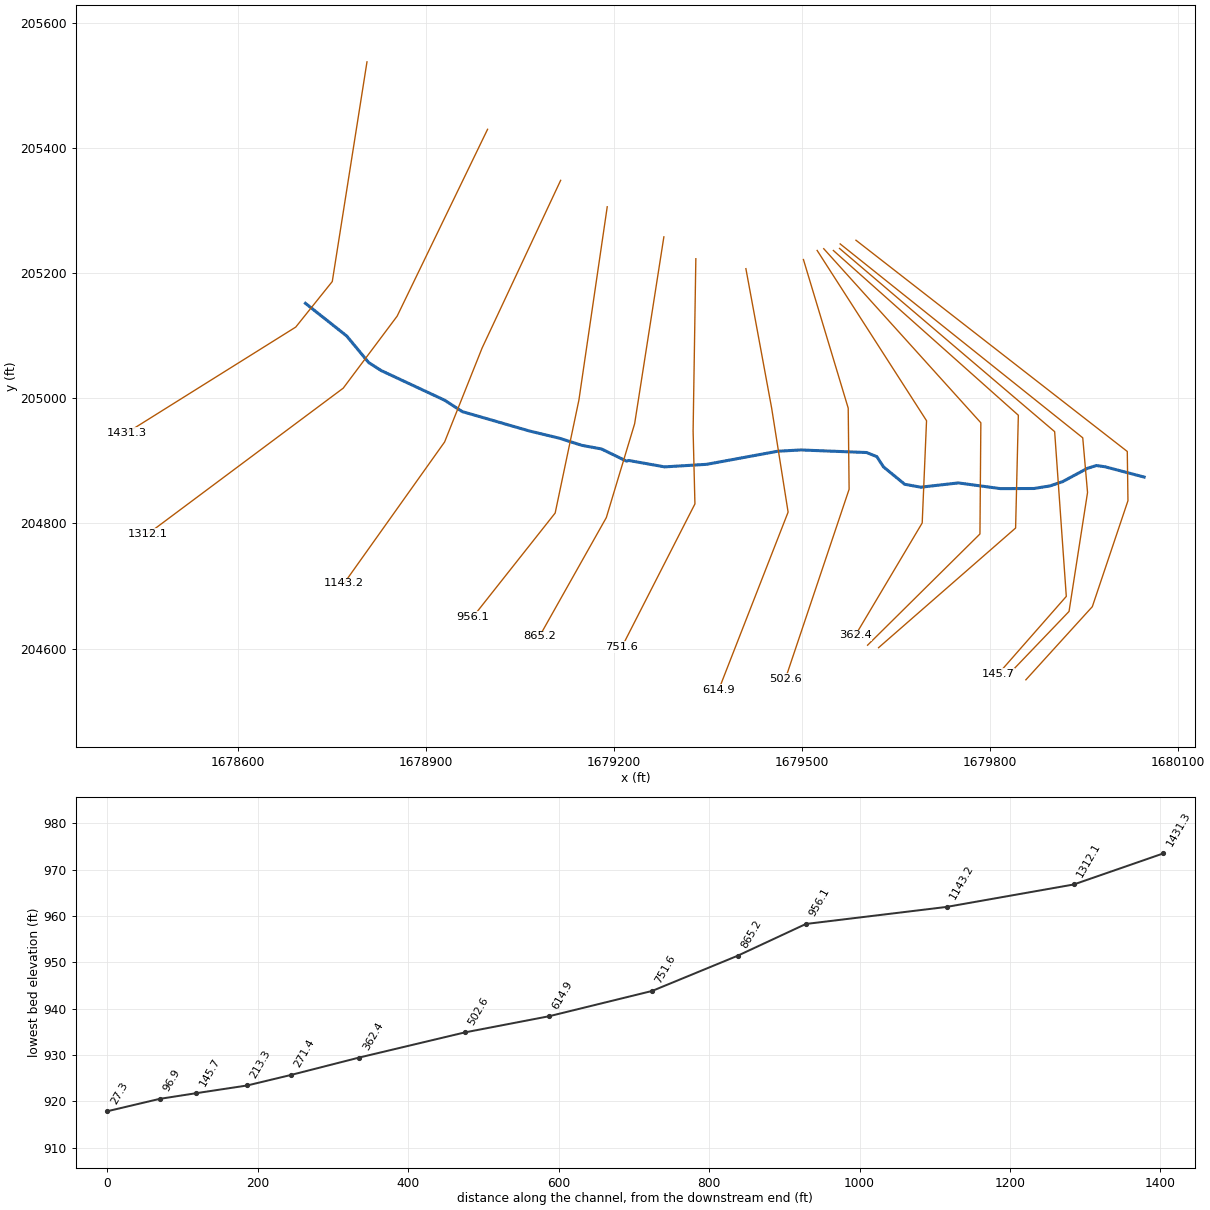
--- lftfrklmcr.prj (project) ---

Proj Title=lftfrklmcr
Current Plan=p01
Default Exp/Contr=0,0
English Units
Geom File=g01
Flow File=f01
Plan File=p01
BEGIN DESCRIPTION:
END DESCRIPTION:
DSS Export Rating Curves= 0
DSS Export Rating Curve Sorted= 0
DSS Export Volume Flow Curves= 0
DXF OffsetX= 0
DXF OffsetY= 0
DXF ScaleX= 0
DXF ScaleY= 0

--- lftfrklmcr.p01 (plan) ---

Plan Title=Floodplain
Program Version=4.00
Geom File=g01
Flow File=f01
K Sum by GR=0
Std Step Tol=0.01
Critical Tol=0.01
Num of Std Step Trials=20
Max Error Tol=0.3
Flow Tol Ratio=0.001
Split Flow NTrial=30
Split Flow Tol=0.02
Split Flow Ratio=0.02
Log Output Level=0
Friction Slope Method=1
Unsteady Friction Slope Method=2
Unsteady Bridges Friction Slope Method=1
Global Log Level=0
CheckData=False
Run HTab=0
Run UNet=0
Run PostProcess=0
UNET Theta=0
UNET Theta Warmup=0
UNET ZTol=0
UNET ZSATol=0
UNET MxIter=0
UNET MaxInSteps=0
UNET DtIC=0
UNET DtMin=0
UNET MaxCRTS=0
UNET WFStab=0
UNET SFStab=0
UNET WFX=0
UNET SFX=0
UNET DSS MLevel=0
UNET DZMax Abort=0
UNET Convert EG Bridges=0
UNET Use Existing IB Tables=0
UNET Froude Limit=0
UNET Froude Power=0
Write IC File=0
Echo Input=False
Echo Output=False
Write Detailed=0

--- lftfrklmcr.f01 (steady flow) ---

Flow Title=NFF Regression Equation
Program Version=4.00
Number of Profiles=1
Profile Names=P100yr
River Rch & RM=lftfrklmcr,Main      ,1431.3
     358
River Rch & RM=lftfrklmcr,Main      ,271.4
     371
Boundary for River Rch & Prof#=lftfrklmcr,Main      ,1
Up Type=0
Dn Type=3
Dn Slope=0.029385

--- lftfrklmcr.g01 (geometry) ---

Geom Title=USGS 10m DEM
Program Version=4.00

River Reach=lftfrklmcr      ,Main
Reach XY= 30
     1678707.845      205151.908     1678773.714      205099.675
      1678808.78      205057.176     1678828.713      205044.386
     1678929.803      204997.034      1678958.14      204978.733
      1679065.23      204947.763     1679112.767      204936.289
      1679148.83      204924.814     1679179.975      204919.077
     1679220.057       204899.61     1679223.765      204900.608
     1679280.786      204890.391     1679347.993      204894.489
     1679461.277      204915.421     1679497.981      204917.438
      1679602.89       204913.34     1679619.282      204906.783
     1679629.937      204890.391     1679663.797      204862.575
     1679689.407      204857.905     1679749.207       204864.77
     1679816.562      204855.623     1679869.876      204855.843
     1679895.385      204859.903     1679915.724      204866.827
     1679954.829      204887.895     1679969.361      204892.562
     1679983.287      204890.581     1680045.704        204874.1

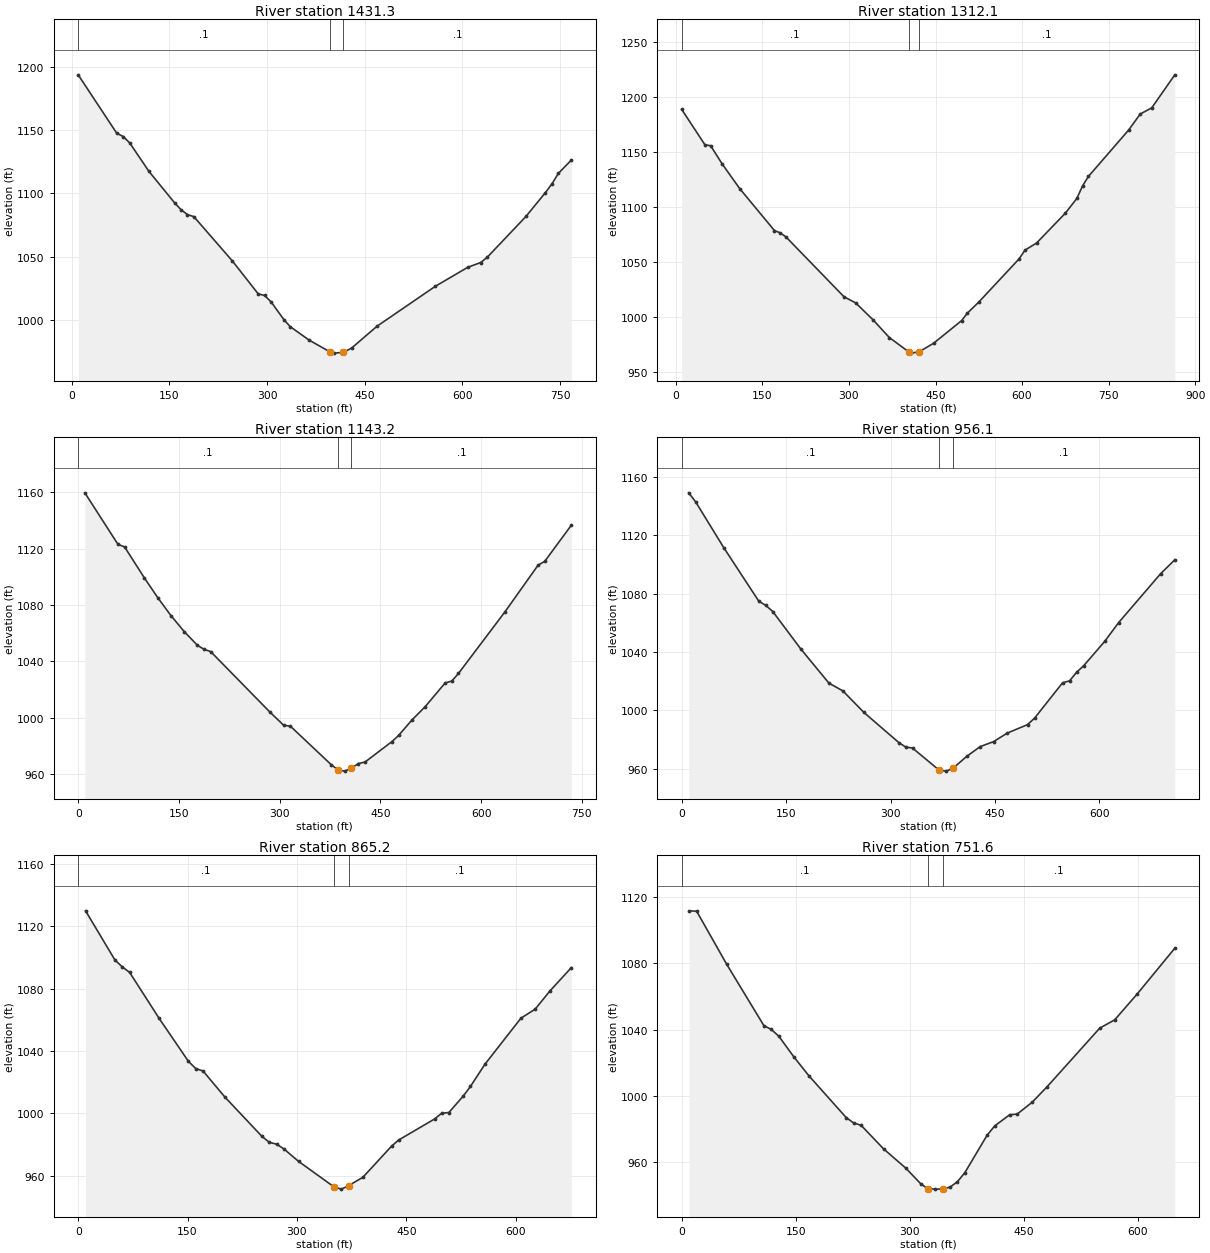
Type RM Length L Ch R = 1 ,1431.3  ,118.2,119.2,120.1
XS GIS Cut Line= 4
     1678806.087      205537.872     1678750.719      205186.718
     1678692.436      205113.864      1678422.57      204944.621
#Sta/Elev= 30
     9.9 1193.91    69.1 1147.67      79 1145.04    88.9 1140.07   118.5 1117.49
     158  1092.5   167.9 1087.04   177.7 1083.25   187.6 1081.57   246.9 1046.39
   286.4 1020.42   296.2 1019.16   306.1 1014.15   325.9  999.98   335.7  994.41
   364.8  983.74  396.12  974.65   402.1   973.5  417.14  974.05   430.1   977.6
   468.7  994.74   558.3 1026.38   608.1 1041.44     628 1045.25   637.9 1049.28
   697.7 1081.78   727.5 1100.63   737.5 1107.52   747.4 1115.84   767.3  1126.4
#Mann= 3 , 0 , 0
     9.9      .1       0  396.12    .045       0  417.14      .1       0
Bank Sta=396.12,417.14
XS Rating Curve= 0 ,0
Exp/Cntr=0.3,0.1

Type RM Length L Ch R = 1 ,1312.1  ,162.3,168.9,175.5
XS GIS Cut Line= 4
     1678998.421      205430.049     1678854.171      205131.349
     1678768.203       205016.24      1678456.39      204783.108
#Sta/Elev= 30
    10.1 1188.47    50.3  1156.3    60.3 1155.36    80.4 1138.73   110.6 1116.44
   170.9 1078.23   180.9 1076.17     191 1072.37   291.5    1018   311.6 1012.48
   341.3  997.32     370  980.96   403.6  967.96   408.3  966.79  422.07  968.13
   446.6  975.72   495.3  996.39   505.3 1003.19   525.3 1013.36   595.2 1052.72
   605.2 1060.48   625.1 1066.89     675 1094.03     695 1107.49     705 1118.99
     715 1127.45   784.8 1169.71   804.8 1184.21   824.8 1189.85   864.7 1219.85
#Mann= 3 , 0 , 0
    10.1      .1       0   403.6    .045       0  422.07      .1       0
Bank Sta=403.6,422.07
XS Rating Curve= 0 ,0
Exp/Cntr=0.3,0.1

Type RM Length L Ch R = 1 ,1143.2  ,182.8,187.1,191.4
XS GIS Cut Line= 4
     1679114.987      205348.453     1678989.679      205080.351
     1678929.939      204930.273     1678769.661      204704.426
#Sta/Elev= 30
     9.9 1159.64    59.2 1123.06    69.1 1121.21    98.6 1099.18   118.4 1085.24
   138.1 1072.45   157.8 1061.12   177.6 1051.32   187.4 1048.48   197.3 1046.86
   286.1 1003.62     306  994.55   316.1  993.85   376.7  966.59   386.9  962.81
   396.9  961.95   406.9  963.98   417.1   967.3   427.2   968.4   467.4  982.99
   477.3  987.33     497  998.26   516.8 1007.75   546.5 1024.59   556.4 1025.93
   566.3 1031.32   635.5 1075.04     685  1108.3   694.8 1110.95   734.4 1136.62
#Mann= 3 , 0 , 0
       0      .1       0   386.9    .045       0   406.9      .1       0
Bank Sta=386.9,406.9
XS Rating Curve= 0 ,0
Exp/Cntr=0.3,0.1

Type RM Length L Ch R = 1 ,956.1   ,93.1,90.9,88.8
XS GIS Cut Line= 4
     1679189.298      205306.198     1679144.128      204997.298
     1679106.244      204816.621     1678975.108      204650.515
#Sta/Elev= 30
    10.1 1149.27    20.1 1143.05    60.4 1111.68   110.8 1074.89   120.8 1072.04
   130.9 1067.79   171.2 1042.06   211.5 1018.68   231.6 1013.32   261.8  998.54
   312.2  977.77   321.9  974.78   331.6  974.11   370.2  958.82   380.2  958.27
   390.2   960.4   409.3  968.32   428.8  975.09   448.2  978.55   467.6  984.35
   496.8  990.18   506.9   994.6   547.2  1018.9   557.3 1020.24   567.3 1026.12
   577.4 1030.54   607.6 1047.25   627.8 1060.27   688.3  1093.9   708.4 1103.32
#Mann= 3 , 0 , 0
       0      .1       0   370.2    .045       0   390.2      .1       0
Bank Sta=370.2,390.2
XS Rating Curve= 0 ,0
Exp/Cntr=0.3,0.1

Type RM Length L Ch R = 1 ,865.2   ,105,113.6,122.1
XS GIS Cut Line= 4
     1679279.636      205258.114      1679233.01      204959.414
     1679187.841      204809.335     1679081.474      204619.916
#Sta/Elev= 30
    10.1 1129.91    50.4 1098.36    60.5 1093.93    70.5 1090.46   110.8 1061.06
   151.2 1033.36   161.2 1028.76   171.3 1027.15   201.5 1010.28   251.9   985.3
     262  981.44   272.1  980.23   282.2  977.17   302.3  969.17   351.1  952.75
   361.1   951.4   371.1   953.7   390.5  959.01   429.7  978.93   439.5   982.9
   488.7  996.37   498.5 1000.04   508.4 1000.55   528.2 1011.16     538 1017.29
   557.8 1031.49   607.2 1061.04   626.9 1066.91   646.7 1078.38   676.3 1093.46
#Mann= 3 , 0 , 0
       0      .1       0   351.1    .045       0   371.1      .1       0
Bank Sta=351.1,371.1
XS Rating Curve= 0 ,0
Exp/Cntr=0.3,0.1

Type RM Length L Ch R = 1 ,751.6   ,133.5,136.8,140.1
XS GIS Cut Line= 4
     1679330.634      205223.144     1679326.263      204947.757
     1679329.177      204831.191     1679212.611      204602.431
#Sta/Elev= 30
     9.8 1111.69    19.7 1111.43      59 1079.63   108.2 1042.41     118 1040.11
   127.9    1036   147.5 1023.64   167.2 1012.28   216.4     987   226.2  983.76
   236.1   982.3   265.6  968.12   294.9  956.46   314.3  947.16   323.7  944.03
   333.7  943.81   343.7   943.9   353.2  945.05   362.9  948.34   372.6  953.76
   401.9  976.35   411.8  981.91   431.5  988.67   441.4  989.08   461.1  996.19
   480.9 1005.62     550 1040.91   569.8 1045.95   599.4 1061.57   648.8 1089.13
#Mann= 3 , 0 , 0
       0      .1       0   323.7    .045       0   343.7      .1       0
Bank Sta=323.7,343.7
XS Rating Curve= 0 ,0
Exp/Cntr=0.3,0.1

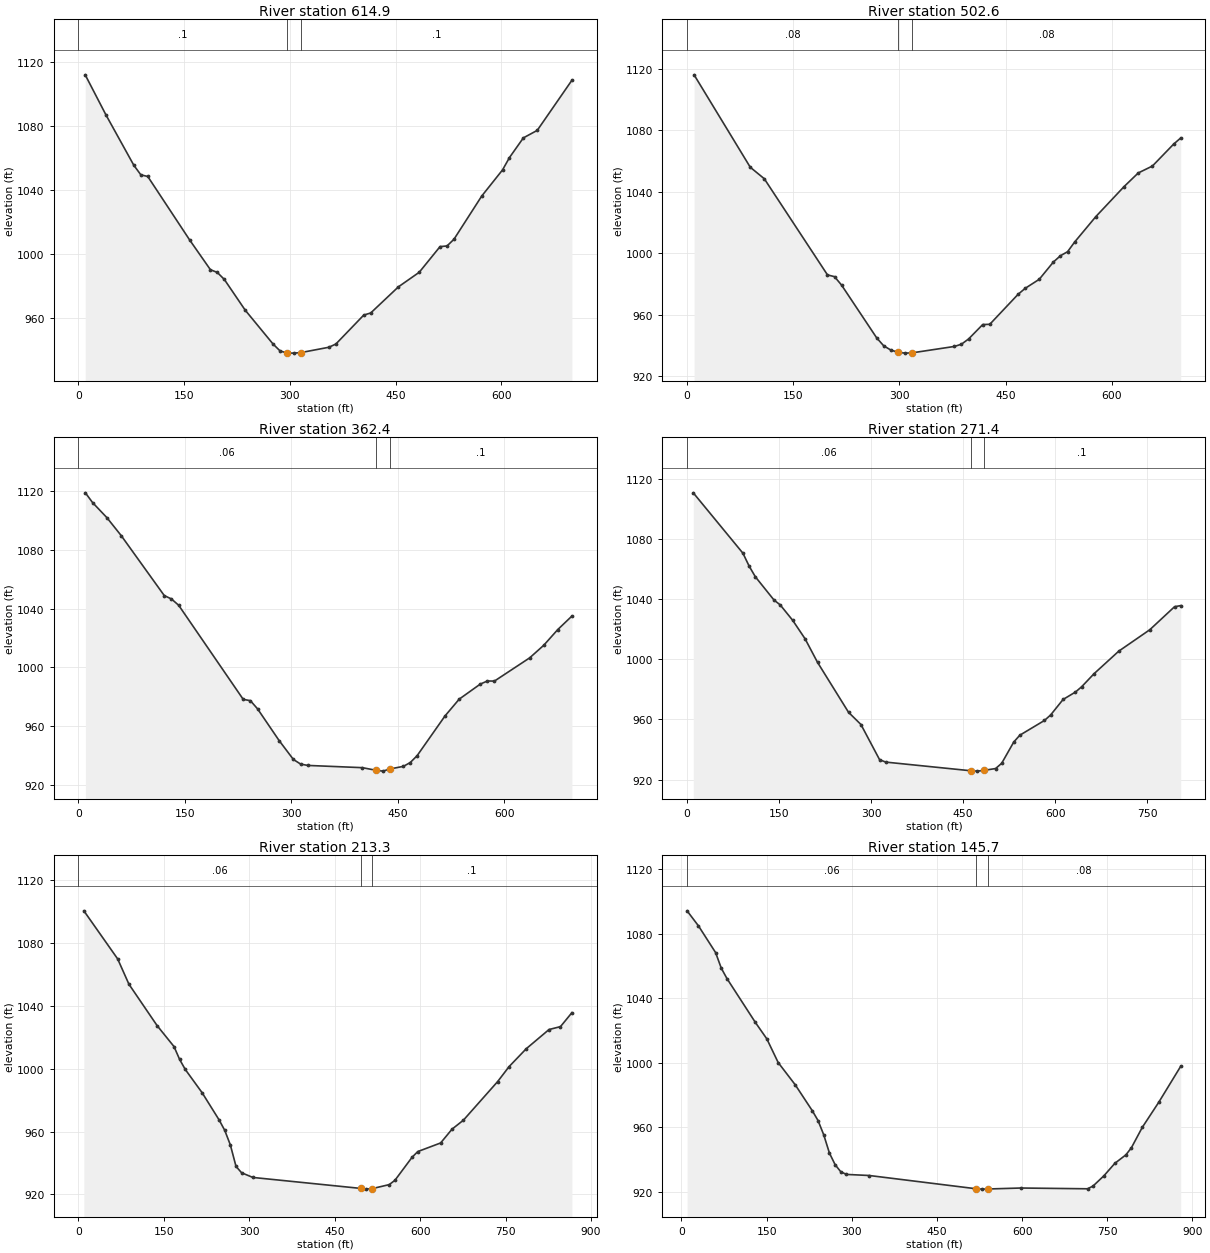
Type RM Length L Ch R = 1 ,614.9   ,115.9,112.2,108.6
XS GIS Cut Line= 4
     1679410.465      205207.259     1679451.571      204984.184
     1679477.798      204818.078     1679367.061      204533.948
#Sta/Elev= 30
     9.9 1111.83    39.4 1086.78    78.9 1055.41    88.8 1049.49    98.6 1048.47
   157.8 1009.02   187.4  990.37   197.2  988.65   207.1  984.32   236.7  965.17
   276.3  943.99   286.2  939.74     296  938.41     306  938.36     316  938.72
   355.4  942.02   365.3  944.04   404.8  962.07   414.7  963.39     454  979.69
   483.5  988.76     513 1004.76   522.9 1005.16   532.7 1009.32   572.1 1036.28
   601.6 1052.57   611.4 1060.25   631.1 1072.52   650.8 1077.21   699.9 1108.42
#Mann= 3 , 0 , 0
       0      .1       0     296    .045       0     316      .1       0
Bank Sta=296,316
XS Rating Curve= 0 ,0
Exp/Cntr=0.3,0.1

Type RM Length L Ch R = 1 ,502.6   ,141.9,140.3,138.7
XS GIS Cut Line= 4
     1679502.261      205221.829     1679573.658      204984.327
     1679575.115      204854.647     1679473.427      204551.433
#Sta/Elev= 30
     9.9 1116.08    89.3 1055.89   109.1 1048.41   198.4  985.79   208.3  984.66
   218.2  979.21     268  944.73   277.9  939.59   287.9  936.86   297.9  935.45
   307.9  934.86   317.9  935.04   377.7  939.21   387.7  940.68   397.7  944.06
   417.7  953.46   427.7  953.63   467.6  973.11   477.6  977.01   497.6  982.94
   517.6   994.2   527.6   998.3   537.6 1000.89   547.6  1007.2   577.6 1023.79
   617.5 1043.33   637.5 1052.19   657.5 1056.69   687.5 1070.98   697.5 1074.97
#Mann= 3 , 0 , 0
       0     .08       0   297.9    .045       0   317.9     .08       0
Bank Sta=297.9,317.9
XS Rating Curve= 0 ,0
Exp/Cntr=0.3,0.1

Type RM Length L Ch R = 1 ,362.4   ,90.1,91,91.9
XS GIS Cut Line= 4
     1679524.117        205236.4     1679698.602      204964.201
     1679691.681      204800.735     1679585.314      204621.515
#Sta/Elev= 30
    10.1 1118.73    20.2 1112.11    40.4 1101.84    60.6 1089.59   121.2 1048.85
   131.3 1046.54   141.5 1042.25   232.4  978.25   242.5  977.36   252.6   971.8
   282.9  950.27   303.1  937.35   313.2  934.25   323.3  933.32   400.3  931.79
   419.2  930.03   429.2  929.44   439.2  930.91   458.1   932.7   467.7   935.3
   477.3  939.93   516.7  967.03   536.6   978.4   566.3  988.64   576.3  990.75
   586.2  990.68   635.8 1006.46   655.6    1015   675.5 1025.76   695.3 1034.88
#Mann= 3 , 0 , 0
       0     .06       0   419.2    .045       0   439.2      .1       0
Bank Sta=419.2,439.2
XS Rating Curve= 0 ,0
Exp/Cntr=0.3,0.1

Type RM Length L Ch R = 1 ,271.4   ,58.5,58,57.6
XS GIS Cut Line= 4
     1679534.624      205239.172     1679785.241      204960.871
     1679783.784      204783.108     1679604.564      204605.345
#Sta/Elev= 30
    10.1  1110.7    91.1 1070.52   101.2 1061.94   111.3 1054.88   141.7 1039.42
   151.8 1036.19   172.1 1025.96   192.3 1013.68   212.6  998.02   263.2  964.78
   283.4  956.67   313.8  933.28   323.9  931.67   463.3  925.88   473.3  925.67
   483.3  926.14   502.9  927.38   512.8  930.86   532.5  945.01   542.4  949.55
   582.6  959.37   592.7  963.04   612.9  973.31   633.1  978.25   643.2  981.77
   663.4  990.44   703.7 1005.44   754.2 1019.65   794.6 1034.97   804.7 1035.72
#Mann= 3 , 0 , 0
       0     .06       0   463.3    .045       0   483.3      .1       0
Bank Sta=463.3,483.3
XS Rating Curve= 0 ,0
Exp/Cntr=0.3,0.1

Type RM Length L Ch R = 1 ,213.3   ,65.5,67.6,69.9
XS GIS Cut Line= 4
      1679549.98      205236.309     1679845.038      204972.943
     1679840.666       204792.63     1679622.105      204601.389
#Sta/Elev= 30
     9.9 1100.25    69.2 1069.71      89 1053.61   138.4 1027.33   168.1 1013.99
     178 1005.78   187.9  999.43   217.5  984.63   247.2  967.41   257.1  960.78
     267  951.47   276.9  937.86   286.7   933.8   306.5  930.83   495.7  923.87
   505.7  923.41   515.7  923.72   545.8  926.28   555.8  929.03   585.9  943.67
   595.9  947.28     636  952.75     656  961.52     676  967.24   736.1  991.78
   756.1 1001.26   786.2 1012.62   826.2 1024.82   846.3 1026.67   866.3 1035.51
#Mann= 3 , 0 , 0
       0     .06       0   495.7    .045       0   515.7      .1       0
Bank Sta=495.7,515.7
XS Rating Curve= 0 ,0
Exp/Cntr=0.3,0.1

Type RM Length L Ch R = 1 ,145.7   ,48.4,48.7,48.6
XS GIS Cut Line= 4
     1679559.816      205239.588     1679902.956      204946.716
     1679921.534       204683.35     1679813.346      204559.863
#Sta/Elev= 30
      10 1094.35    30.1 1084.99    60.2 1068.47    70.2 1058.81    80.2 1052.36
   130.3 1025.11   150.4 1014.97   170.4 1000.27   200.5  986.43   230.6  970.33
   240.6  964.29   250.6  955.48   260.7  944.09   270.7  936.92   280.7   932.5
   290.7  930.87   330.8   930.2   519.6  921.95   529.4  921.75   539.1  921.83
   597.8  922.44   715.2  921.96   724.8  923.64   744.1  930.05   763.4  937.79
   782.8  943.03   792.4   947.4   811.7  960.12   840.7  975.68   879.3  997.95
#Mann= 3 , 0 , 0
      10     .06       0   519.6    .045       0   539.1     .08       0
#XS Ineff= 2 , 0
       0                     615       0
Permanent Ineff=
       F       F
Bank Sta=519.6,539.1
XS Rating Curve= 0 ,0
Exp/Cntr=0.3,0.1

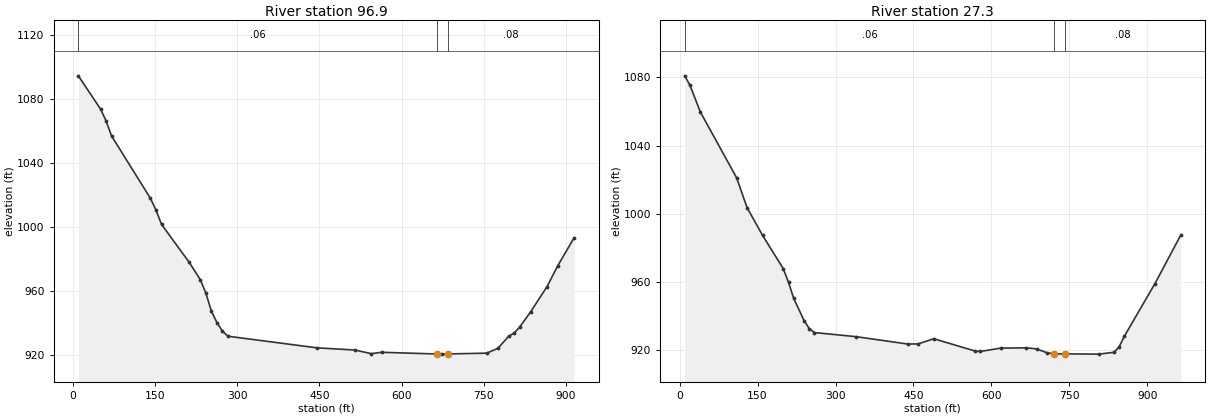
Type RM Length L Ch R = 1 ,96.9    ,71.1,69.6,68.4
XS GIS Cut Line= 5
     1679560.851      205246.822     1679947.761      204936.881
     1679955.411      204849.456     1679925.905      204659.308
     1679829.739       204558.77
#Sta/Elev= 30
    10.1 1094.68    50.6 1073.91    60.7 1066.53    70.8 1057.02   141.6 1018.07
   151.8 1010.71   161.9 1001.75   212.5  977.95   232.7  967.12   242.8  958.78
   252.9  947.48     263  940.31   273.2  934.84   283.3  931.72   445.2  924.47
   515.2  923.07   544.5  920.81     564  921.67   664.7   920.6   674.7  920.52
   684.7  920.64   755.7  921.12   775.9  924.18   795.8  931.75   805.7  933.73
   815.7  937.47   835.6  946.99   865.4  962.65   885.2  975.85   915.1  993.39
#Mann= 3 , 0 , 0
    10.1     .06       0   664.7    .045       0   684.7     .08       0
#XS Ineff= 2 , 0
       0                     719       0
Permanent Ineff=
       F       F
Bank Sta=664.7,684.7
XS Rating Curve= 0 ,0
Exp/Cntr=0.3,0.1

Type RM Length L Ch R = 1 ,27.3    ,34.3,27.3,20.4
XS GIS Cut Line= 5
     1679586.043      205252.701     1680018.794      204915.025
     1680019.887      204836.343     1679963.061      204666.958
     1679857.059      204550.028
#Sta/Elev= 30
      10  1080.9      20 1075.32    39.9 1059.74   109.8 1021.11   129.7 1003.75
   159.7  987.41   199.6  967.85   209.6  959.87   219.6  950.45   239.5  937.54
   249.5  932.77   259.5  930.48   339.3  928.09   439.1  923.76   459.1  923.83
     489  926.87   568.6  919.66   578.4  919.39   617.8  921.37   667.3  921.53
   687.2  920.89     707  918.66  720.89  917.99  742.29     918   806.3  917.85
   835.9  918.91   845.7  922.09   855.6  928.21   914.8  959.22   964.1  987.43
#Mann= 3 , 0 , 0
      10     .06       0  720.89    .045       0  742.29     .08       0
Bank Sta=720.89,742.29
XS Rating Curve= 0 ,0
Exp/Cntr=0.3,0.1

Chan Stop Cuts=-1
Use User Specified Reach Order=0